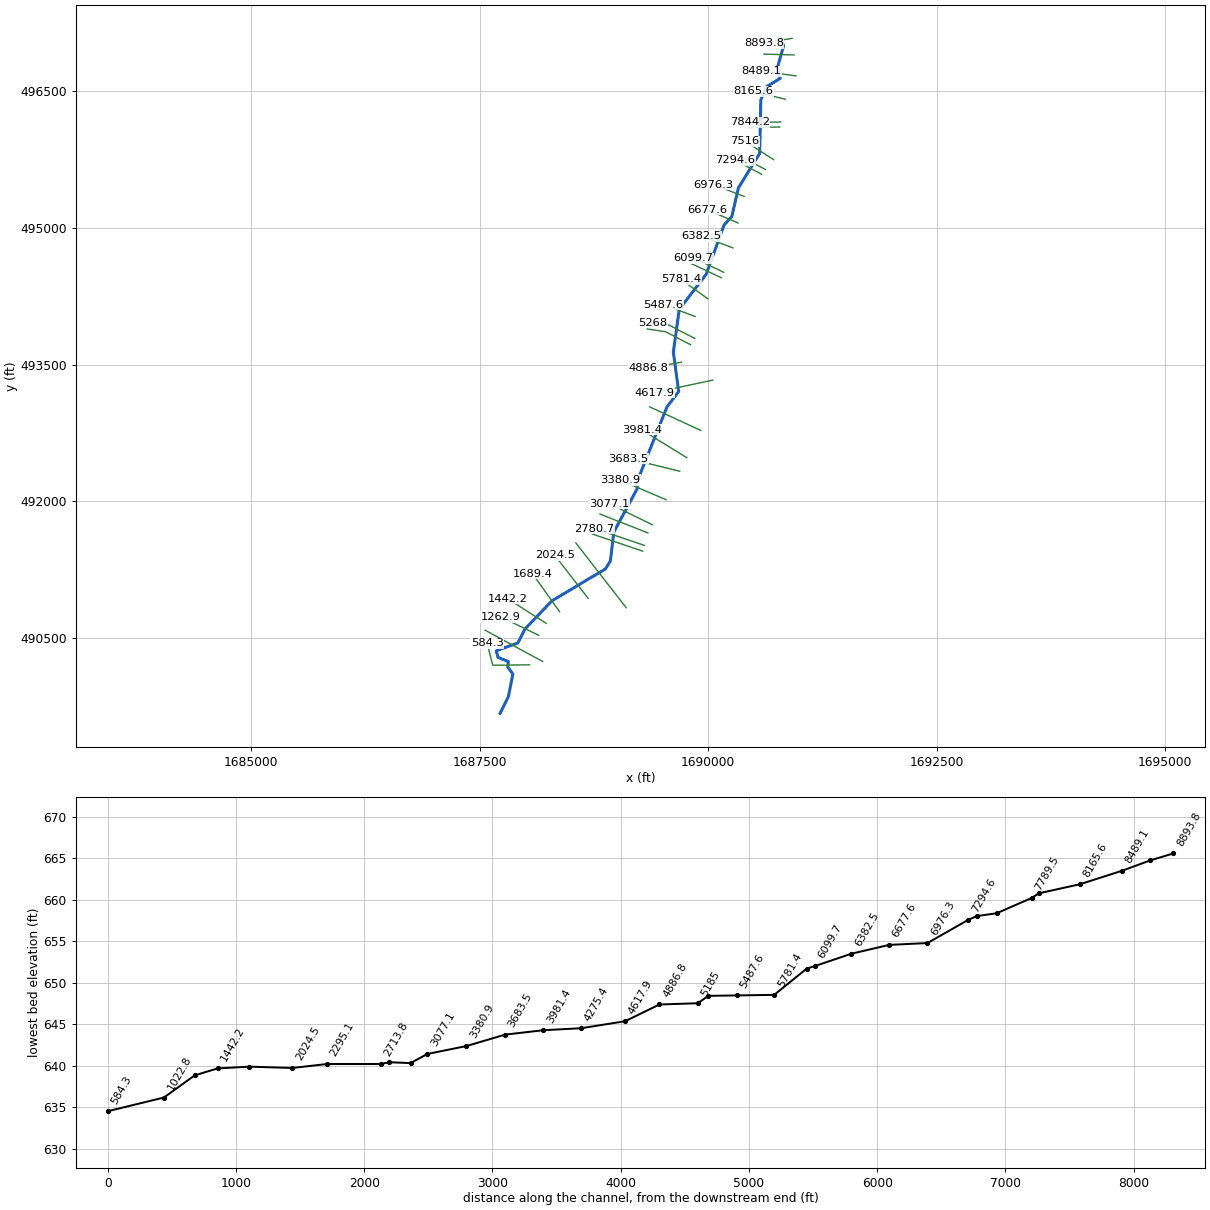
--- LickCk.prj (project) ---

Proj Title=LickCk
Current Plan=p01
Default Exp/Contr=0,0
English Units
Geom File=g01
Flow File=f01
Plan File=p01
BEGIN DESCRIPTION:
AMEC Environment & Infrastructure, 2013
Projection: NAD 1983 State Plane West Virginia South FIPS 4702 (US Feet)
Vertical Datum: NAVD 1988
END DESCRIPTION:
DSS Export Rating Curves= 0
DSS Export Rating Curve Sorted= 0
DSS Export Volume Flow Curves= 0
DXF OffsetX= 0
DXF OffsetY= 0
DXF ScaleX= 0
DXF ScaleY= 0

--- LickCk.p01 (plan) ---

Plan Title=Floodplain
Program Version=4.00
Geom File=g01
Flow File=f01
K Sum by GR=0
Std Step Tol=0.01
Critical Tol=0.01
Num of Std Step Trials=20
Max Error Tol=0.3
Flow Tol Ratio=0.001
Split Flow NTrial=30
Split Flow Tol=0.02
Split Flow Ratio=0.02
Log Output Level=0
Friction Slope Method=1
Unsteady Friction Slope Method=2
Unsteady Bridges Friction Slope Method=1
Global Log Level=0
CheckData=False
Run HTab=0
Run UNet=0
Run PostProcess=0
UNET Theta=0
UNET Theta Warmup=0
UNET ZTol=0
UNET ZSATol=0
UNET MxIter=0
UNET MaxInSteps=0
UNET DtIC=0
UNET DtMin=0
UNET MaxCRTS=0
UNET WFStab=0
UNET SFStab=0
UNET WFX=0
UNET SFX=0
UNET DSS MLevel=0
UNET DZMax Abort=0
UNET Convert EG Bridges=0
UNET Use Existing IB Tables=0
UNET Froude Limit=0
UNET Froude Power=0
Write IC File=0
Echo Input=False
Echo Output=False
Write Detailed=0

--- LickCk.f01 (steady flow) ---

Flow Title=USGS Regress. Eqn. (2010) - Western-Plateaus
Program Version=4.10
Number of Profiles= 1
Profile Names=P100yr
River Rch & RM=LickCk,Main            ,8893.8
     879
River Rch & RM=LickCk,Main            ,7516
     935
River Rch & RM=LickCk,Main            ,5487.6
    1022
River Rch & RM=LickCk,Main            ,4275.4
    1111
River Rch & RM=LickCk,Main            ,2295.1
    1263
River Rch & RM=LickCk,Main            ,1689.4
    1335
River Rch & RM=LickCk,Main            ,584.3
    1349
Boundary for River Rch & Prof#=LickCk,Main            , 1
Up Type= 0
Dn Type= 3
Dn Slope=0.004
DSS Import GetInterval= 0
DSS Import GetPeak= 0
DSS Import FillOption= 0

--- LickCk.g01 (geometry) ---

Geom Title=USGS 3m DEM
Program Version=4.10

River Reach=LickCk          ,Main
Reach XY= 30
     1690795.774      497065.509     1690825.288      496996.933
     1690759.547      496761.523     1690788.193      496639.127
     1690638.453      496548.416      1690576.04       496403.75
     1690563.673      495816.348     1690330.641      495438.837
      1690259.46      495126.771     1690173.523      495030.851
     1689978.116      494491.272     1689683.533      494106.324
     1689618.949      493638.095     1689677.283      493206.064
     1689549.158      493036.793     1689212.022      492191.446
     1689228.515      492150.213     1688968.019      491665.223
     1688929.543       491346.43     1688874.855      491259.451
     1688290.223       490910.89     1687994.473      490600.597
      1687917.39      490448.253     1687680.931      490363.357
     1687700.202      490290.961     1687813.744      490244.607
     1687807.494      490185.232     1687862.702      490106.684
     1687814.751      489863.107     1687722.941      489676.571

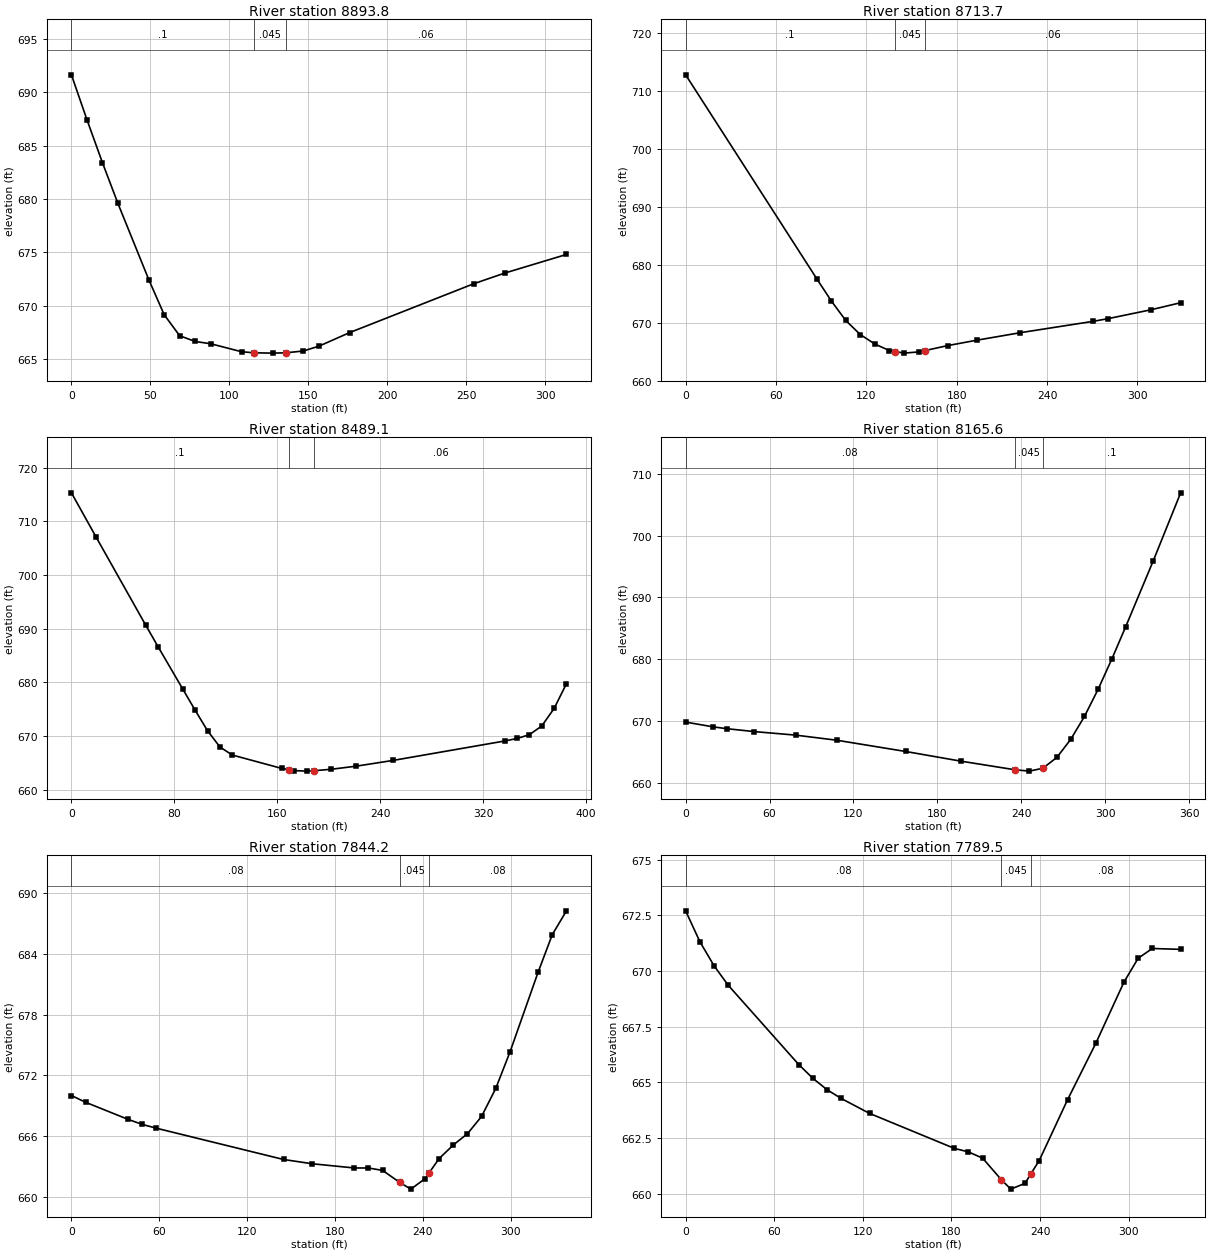
Type RM Length L Ch R = 1 ,8893.8  ,184.8,180.1,175.4
XS GIS Cut Line= 2
     1690918.109      497078.768     1690609.354      497025.678
#Sta/Elev= 19
       0  691.63     9.8  687.44    19.6  683.42    29.4   679.6      49  672.44
    58.7  669.17    68.5   667.2    78.3  666.66    88.1  666.45   107.7   665.7
   115.7   665.6   127.3  665.57   135.7   665.6   146.8  665.77   156.6  666.22
   176.2   667.5   254.5  672.06   274.1  673.06   313.3  674.81
#Mann= 3 , 0 , 0
       0      .1       0   115.7    .045       0   135.7     .06       0
Bank Sta=115.7,135.7
XS Rating Curve= 0 ,0
Exp/Cntr=0.3,0.1

Type RM Length L Ch R = 1 ,8713.7  ,225.5,224.6,219.7
XS GIS Cut Line= 2
      1690939.27      496896.664     1690610.725      496905.388
#Sta/Elev= 18
       0  712.76      87  677.59    96.7  673.75   106.3  670.37     116  667.93
   125.7  666.29   135.3  665.17   138.9  665.01     145  664.73   154.7  664.94
   158.9  665.17     174  666.03   193.3  666.96   222.3  668.26   270.7  670.22
   280.3  670.67   309.3  672.23   328.7  673.43
#Mann= 3 , 0 , 0
       0      .1       0   138.9    .045       0   158.9     .06       0
Bank Sta=138.9,158.9
XS Rating Curve= 0 ,0
Exp/Cntr=0.3,0.1

Type RM Length L Ch R = 1 ,8489.1  ,324,323.6,320.5
XS GIS Cut Line= 2
     1690960.832      496666.826     1690579.567      496718.393
#Sta/Elev= 23
       0  715.31    19.2  707.06    57.7  690.67    67.3  686.65    86.6  678.72
    96.2  674.79   105.8  670.98   115.4  667.96     125  666.46   163.5  663.96
   168.9  663.74   173.1  663.56   182.8  663.46   188.9  663.54     202  663.81
   221.2  664.38   250.1  665.46   336.6  669.07   346.3  669.54   355.9  670.25
   365.5  671.87   375.1  675.13   384.7  679.75
#Mann= 3 , 0 , 0
       0      .1       0   168.9    .045       0   188.9     .06       0
Bank Sta=168.9,188.9
XS Rating Curve= 0 ,0
Exp/Cntr=0.3,0.1

Type RM Length L Ch R = 1 ,8165.6  ,315.7,321.4,326.8
XS GIS Cut Line= 2
     1690842.364      496411.168      1690498.69      496496.198
#Sta/Elev= 19
       0   669.8    19.7  669.03    29.5  668.73    49.2  668.26    78.7  667.69
   108.2  666.86   157.4  665.04   196.7  663.48   235.5  662.08   245.9  661.86
   255.5  662.33   265.5  664.09   275.4  667.01   285.2  670.72     295  675.13
   304.9  680.08   314.7  685.25   334.4  695.92     354  706.93
#Mann= 3 , 0 , 0
       0     .08       0   235.5    .045       0   255.5      .1       0
Bank Sta=235.5,255.5
XS Rating Curve= 0 ,0
Exp/Cntr=0.3,0.1

Type RM Length L Ch R = 1 ,7844.2  ,54.6,54.7,54.6
XS GIS Cut Line= 2
      1690791.86      496160.906     1690453.686      496156.899
#Sta/Elev= 23
       0  670.01     9.7  669.34    38.6  667.66    48.3  667.16      58  666.78
   144.9  663.69   164.3  663.27   193.3  662.85   202.9  662.85   212.6  662.61
   224.2  661.43   231.9  660.76   241.6  661.79   244.2  662.33   251.2  663.78
   260.9  665.12   270.6  666.24   280.2  667.94   289.9  670.71   299.6   674.3
   318.9  682.22   328.5   685.9   338.2  688.26
#Mann= 3 , 0 , 0
       0     .08       0   224.2    .045       0   244.2     .08       0
Bank Sta=224.2,244.2
XS Rating Curve= 0 ,0
Exp/Cntr=0.3,0.1

Type RM Length L Ch R = 1 ,7789.5  ,285.8,273.5,258.4
XS GIS Cut Line= 2
     1690782.737      496106.159      1690447.61      496102.187
#Sta/Elev= 23
       0   672.7     9.6  671.32    19.2  670.24    28.7  669.37    76.6   665.8
    86.2  665.18    95.8  664.67   105.3  664.28   124.5  663.61   181.9  662.04
   191.5  661.88   201.1   661.6   213.8  660.63   220.2  660.21   229.8  660.47
   233.8   660.9   239.4  661.49   258.6  664.22   277.7  666.75   296.8   669.5
   306.4  670.57     316  671.01   335.2  670.97
#Mann= 3 , 0 , 0
       0     .08       0   213.8    .045       0   233.8     .08       0
Bank Sta=213.8,233.8
XS Rating Curve= 0 ,0
Exp/Cntr=0.3,0.1

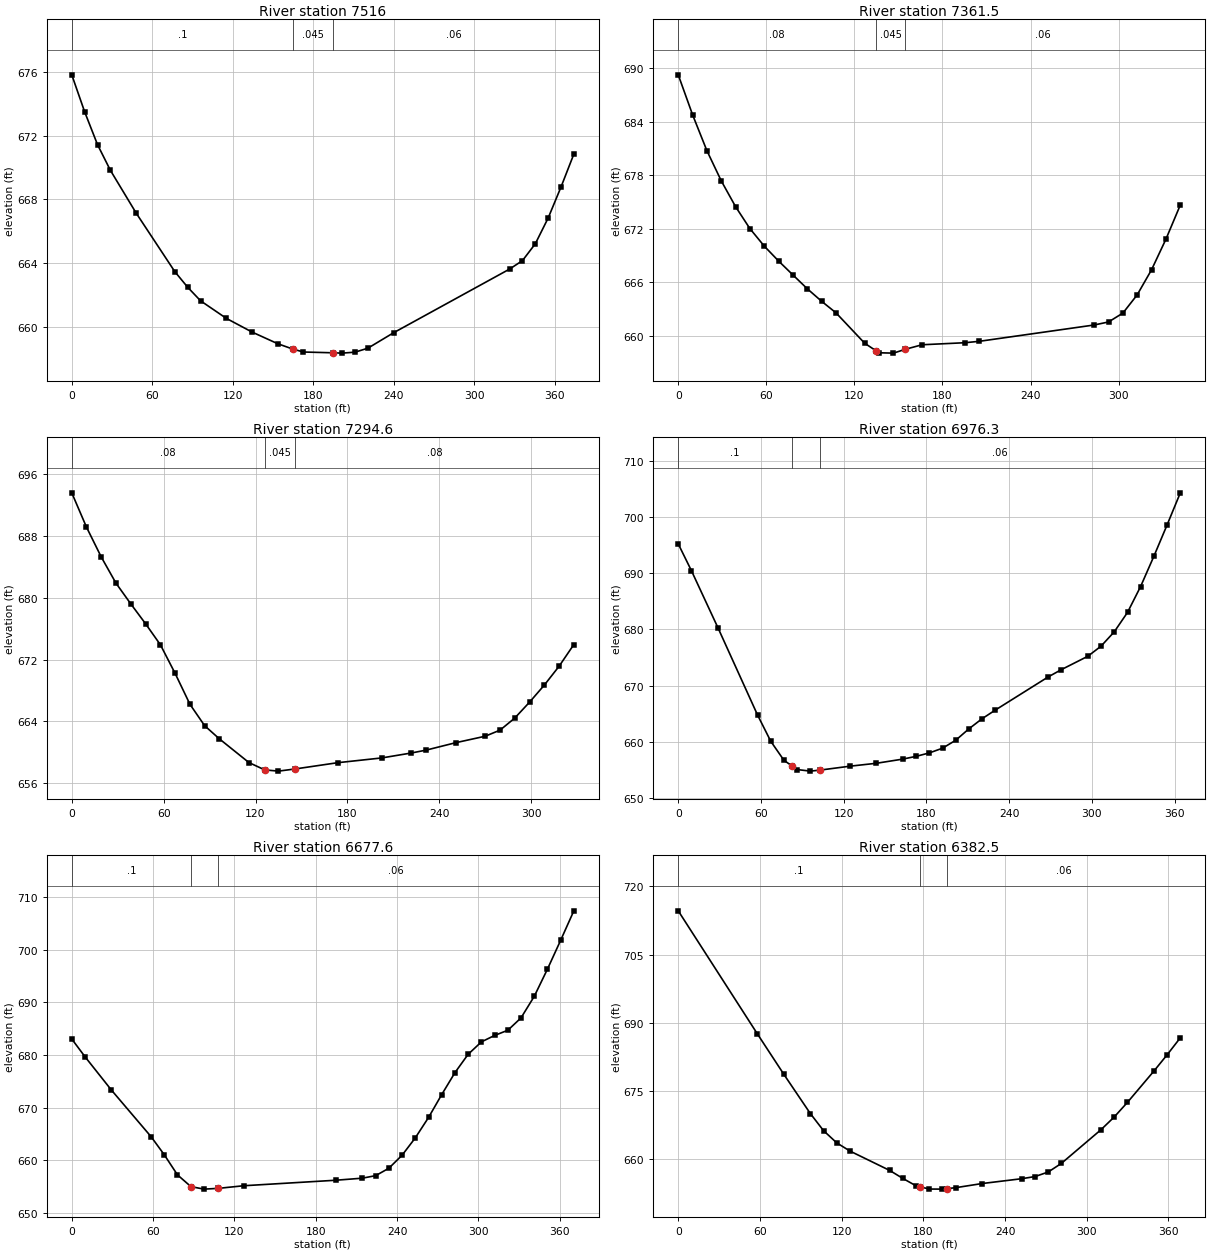
Type RM Length L Ch R = 1 ,7516    ,151.7,154.5,155.6
XS GIS Cut Line= 2
     1690716.717      495748.148     1690401.674      495950.169
#Sta/Elev= 24
       0  675.81     9.6  673.49    19.2  671.43    28.8  669.82      48  667.14
    76.8  663.47    86.4  662.49      96  661.64   115.2  660.54   134.4  659.68
   153.5  658.95     165 658.607   172.7  658.43     195  658.38   201.5  658.36
   211.1  658.42   220.7  658.67   239.9  659.64   326.3  663.63   335.9  664.16
   345.5  665.22   355.1  666.84   364.7  668.79   374.2  670.84
#Mann= 3 , 0 , 0
       0      .1       0     165    .045       0     195     .06       0
Bank Sta=165,195
XS Rating Curve= 0 ,0
Exp/Cntr=0.3,0.1

Type RM Length L Ch R = 1 ,7361.5  ,66.1,66.9,66.2
XS GIS Cut Line= 2
     1690627.317      495640.556      1690324.31      495799.067
#Sta/Elev= 27
       0  689.28     9.8  684.78    19.5  680.77    29.3  677.37    39.1  674.46
    48.8  672.01    58.6  670.04    68.4  668.36    78.2  666.79    87.9  665.25
    97.7  663.84   107.5  662.54     127  659.13   134.6658.3002   136.8  658.06
   146.6  658.02   154.6658.4469   166.1  658.96   195.4  659.19   205.2  659.35
   283.3  661.18   293.1  661.52   302.9  662.52   312.6  664.56   322.4  667.38
   332.2  670.82     342  674.66
#Mann= 3 , 0 , 0
       0     .08       0   134.6    .045       0   154.6     .06       0
Bank Sta=134.6,154.6
XS Rating Curve= 0 ,0
Exp/Cntr=0.3,0.1

Type RM Length L Ch R = 1 ,7294.6  ,314.6,318.3,319.8
XS GIS Cut Line= 2
     1690584.418      495588.927     1690293.887      495740.912
#Sta/Elev= 27
       0  693.62     9.6  689.18    19.3  685.29    28.9  681.91    38.6  679.22
    48.2  676.66    57.9  673.93    67.5  670.23    77.2  666.22    86.8  663.45
    96.4  661.75   115.7  658.68     126657.7303     135  657.57     146657.8547
   173.6  658.66   202.5  659.28   221.8  659.92   231.4  660.29   250.7  661.25
     270  662.09   279.7  662.88   289.3  664.44     299  666.51   308.6  668.71
   318.2  671.14   327.9  673.97
#Mann= 3 , 0 , 0
       0     .08       0     126    .045       0     146     .08       0
Bank Sta=126,146
XS Rating Curve= 0 ,0
Exp/Cntr=0.3,0.1

Type RM Length L Ch R = 1 ,6976.3  ,299.2,298.7,297.9
XS GIS Cut Line= 2
     1690393.853      495344.848     1690054.054      495475.913
#Sta/Elev= 30
       0  695.23     9.6  690.44    28.8   680.3    57.5  664.78    67.1  660.09
    76.7  656.69    82.7655.6664    86.3  655.05    95.8  654.77   102.7654.9473
   124.6  655.65   143.8  656.17   162.9  656.91   172.5   657.4   182.1  658.01
   191.7  658.85   201.3  660.27   210.8  662.29   220.4   664.1     230  665.64
   268.4  671.55   277.9  672.84   297.1  675.22   306.7  677.02   316.3  679.58
   325.9  683.03   335.4  687.64     345  693.01   354.6   698.6   364.2  704.32
#Mann= 3 , 0 , 0
       0      .1       0    82.7    .045       0   102.7     .06       0
Bank Sta=82.7,102.7
XS Rating Curve= 0 ,0
Exp/Cntr=0.3,0.1

Type RM Length L Ch R = 1 ,6677.6  ,293.2,295.1,295.4
XS GIS Cut Line= 2
     1690327.433      495054.164     1689986.909      495199.887
#Sta/Elev= 28
       0  683.05     9.8  679.67    29.2  673.37    58.5  664.51    68.2  661.09
      78  657.25    87.9655.0296    97.5  654.55   107.9654.6907   126.7  655.19
   194.9  656.24   214.4  656.63   224.2  657.11   233.9  658.51   243.7  660.99
   253.4  664.27   263.2  668.15   272.9  672.49   282.7  676.67   292.4  680.14
   302.2   682.5   311.9  683.72   321.7  684.71   331.4  687.05   341.2  691.15
   350.9   696.3   360.6  701.75   370.4  707.38
#Mann= 3 , 0 , 0
       0      .1       0    87.9    .045       0   107.9     .06       0
Bank Sta=87.9,107.9
XS Rating Curve= 0 ,0
Exp/Cntr=0.3,0.1

Type RM Length L Ch R = 1 ,6382.5  ,283.8,282.7,278.8
XS GIS Cut Line= 2
     1690270.903      494781.225     1689924.641       494907.86
#Sta/Elev= 26
       0  714.59    58.2  687.53    77.6  678.67      97  670.08   106.7  666.32
   116.4  663.64   126.1  661.84   155.2   657.6   164.9  655.84   174.6  654.21
   177.7 653.983   184.4   653.5     194  653.48   197.7653.6014   203.8   653.8
   223.2  654.71   252.3  655.77     262  656.24   271.7  657.24   281.4  659.14
   310.5  666.54   320.2  669.33   329.9  672.54   349.3   679.4     359  682.97
   368.7  686.71
#Mann= 3 , 0 , 0
       0      .1       0   177.7    .045       0   197.7     .06       0
Bank Sta=177.7,197.7
XS Rating Curve= 0 ,0
Exp/Cntr=0.3,0.1

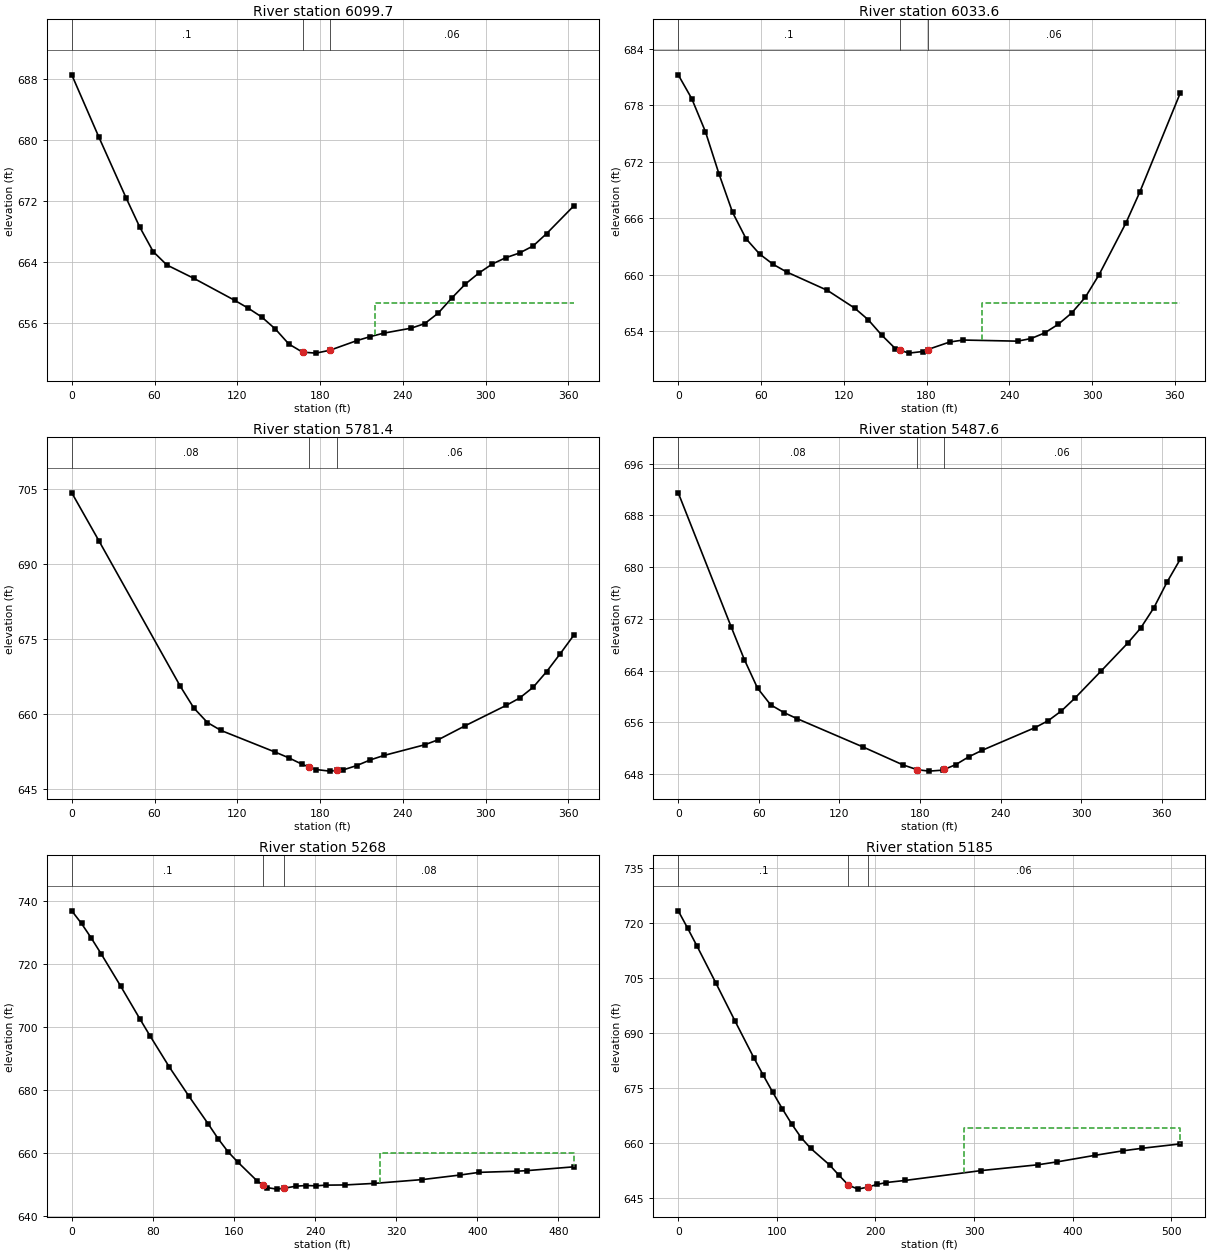
Type RM Length L Ch R = 1 ,6099.7  ,66.1,66.1,66.2
XS GIS Cut Line= 2
     1690170.817      494513.425     1689841.731      494668.984
#Sta/Elev= 30
       0  688.59    19.7  680.38    39.4  672.41    49.2  668.61      59  665.36
    68.9   663.6    88.5  661.84     118  658.96   127.9  657.92   137.7  656.76
   147.6  655.18   157.4   653.2   167.3652.1389   177.1  652.01   187.3652.3967
   206.6  653.65   216.4  654.18   226.3  654.64     246  655.29   255.8  655.88
   265.6  657.26   275.5  659.25   285.3  661.08   295.1  662.53     305  663.74
   314.8  664.56   324.6  665.17   334.5   666.1   344.3  667.73     364  671.37
#Mann= 3 , 0 , 0
       0      .1       0   167.3    .045       0   187.3     .06       0
#XS Ineff= 2 , 0
                          220.02          658.62
Permanent Ineff=
       F       F
Bank Sta=167.3,187.3
XS Rating Curve= 0 ,0
Exp/Cntr=0.3,0.1

Type RM Length L Ch R = 1 ,6033.6  ,254.9,252.2,246.1
XS GIS Cut Line= 2
     1690142.768      494454.087     1689813.682      494609.647
#Sta/Elev= 30
       0  681.23     9.8   678.7    19.7   675.2    29.5  670.73    39.4  666.62
    49.2  663.82      59   662.2    68.9   661.1    78.7  660.29   108.2  658.34
   127.9  656.46   137.7  655.23   147.6  653.58   157.4  652.16   160.8651.9929
   167.2  651.68   177.1  651.85   180.8652.0566   196.8  652.86   206.6  653.07
     246  652.95   255.8  653.23   265.6  653.82   275.5  654.74   285.3  655.95
   295.1  657.61     305  659.98   324.6  665.51   334.5  668.74     364  679.31
#Mann= 3 , 0 , 0
       0      .1       0   160.8    .045       0   180.8     .06       0
#XS Ineff= 2 , 0
                          220.02          657.05
Permanent Ineff=
       F       F
Bank Sta=160.8,180.8
XS Rating Curve= 0 ,0
Exp/Cntr=0.3,0.1

Type RM Length L Ch R = 1 ,5781.4  ,286.3,293.8,299.8
XS GIS Cut Line= 2
     1689998.109      494221.795     1689702.711      494434.482
#Sta/Elev= 26
       0  704.15    19.7  694.55    78.7  665.48    88.5  661.14    98.4  658.23
   108.2  656.66   147.6  652.32   157.4  651.18   167.2  649.87     172649.3768
   177.1  648.85   186.9  648.53     192648.6616   196.8  648.78   206.6  649.64
   216.4  650.77   226.3  651.66   255.8  653.79   265.6  654.79   285.3  657.61
   314.8  661.65   324.6  663.12   334.5  665.29   344.3  668.43   354.2  672.02
     364  675.71
#Mann= 3 , 0 , 0
       0     .08       0     172    .045       0     192     .06       0
Bank Sta=172,192
XS Rating Curve= 0 ,0
Exp/Cntr=0.3,0.1

Type RM Length L Ch R = 1 ,5487.6  ,221.1,219.6,214.7
XS GIS Cut Line= 2
     1689857.741      494028.876     1689507.685      494159.655
#Sta/Elev= 26
       0  691.49    39.3  670.82    49.2  665.71      59   661.3    68.8  658.71
    78.7  657.51    88.5  656.57   137.7  652.18   167.2  649.43     178648.6743
   186.8  648.46   196.7  648.61     198648.7227   206.5  649.46   216.3  650.68
   226.2  651.68   265.5  655.18   275.4  656.26   285.2  657.77     295  659.69
   314.7  663.93   334.4  668.22   344.2  670.58     354  673.71   363.8  677.68
   373.7  681.24
#Mann= 3 , 0 , 0
       0     .08       0     178    .045       0     198     .06       0
Bank Sta=178,198
XS Rating Curve= 0 ,0
Exp/Cntr=0.3,0.1

Type RM Length L Ch R = 1 ,5268    ,82.9,83,84.8
XS GIS Cut Line= 3
     1689852.832      493788.419     1689570.797      493934.889
     1689394.883       493958.15
#Sta/Elev= 30
       0  737.01     9.6  732.98    19.3  728.31    28.9  723.36    48.2  713.05
    67.4  702.48      77   697.3    96.3  687.24   115.6  677.97   134.8  669.06
   144.4  664.44   154.1  660.31   163.7  657.04     183  650.96     189649.6753
   192.6   648.9   202.2  648.41     209648.6919   221.5  649.36   231.1  649.56
   240.8  649.46   250.4  649.68   269.6  649.74   298.5  650.24   345.8  651.45
   383.2  652.91   401.8  653.75   439.2  654.12   448.6  654.29   495.2  655.51
#Mann= 3 , 0 , 0
       0      .1       0     189    .045       0     209     .08       0
#XS Ineff= 2 , 0
                          303.81           659.9
Permanent Ineff=
       F       F
Bank Sta=189,209
XS Rating Curve= 0 ,0
Exp/Cntr=0.3,0.1

Type RM Length L Ch R = 1 ,5185    ,282.6,298.2,312.6
XS GIS Cut Line= 3
     1689806.955      493719.753     1689534.527      493861.233
     1689334.709      493891.854
#Sta/Elev= 27
       0  723.28     9.6  718.52    19.2   713.6    38.4   703.5    57.6  693.27
    76.7  683.26    86.3  678.48    95.9  673.86   105.5  669.41   115.1  665.23
   124.7  661.51   134.3  658.62   153.5  654.09   163.1  651.26   172.6 648.598
   182.3  647.52   192.6648.1038   201.4  648.78     211  649.32   230.2  649.89
     307  652.56   364.7  654.15     384  654.93   422.5  656.72   451.4  657.97
   470.6  658.65   509.1  659.83
#Mann= 3 , 0 , 0
       0      .1       0   172.6    .045       0   192.6     .06       0
#XS Ineff= 2 , 0
                          290.17          664.23
Permanent Ineff=
       F       F
Bank Sta=172.6,192.6
XS Rating Curve= 0 ,0
Exp/Cntr=0.3,0.1

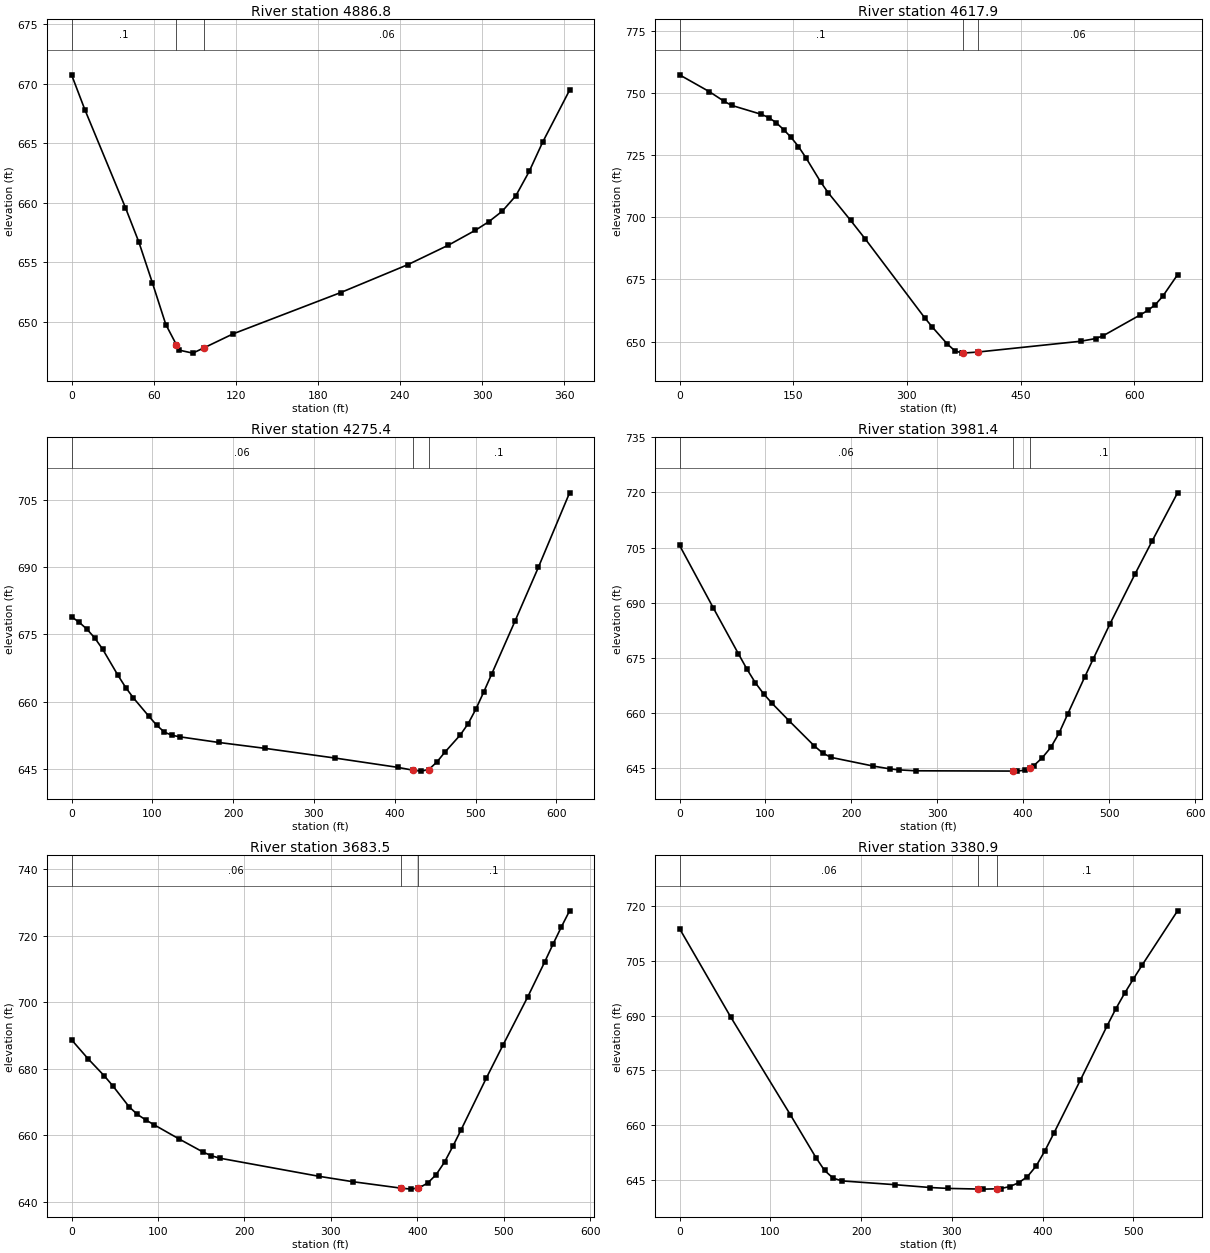
Type RM Length L Ch R = 1 ,4886.8  ,267,268.9,268.4
XS GIS Cut Line= 2
     1689707.267      493527.555     1689348.962      493463.295
#Sta/Elev= 21
       0  670.74     9.8  667.79    39.4  659.58    49.2  656.69      59   653.3
    68.9  649.77    76.6648.0807    78.7  647.62    88.6  647.37    96.6647.8037
   118.1  648.99   196.8  652.46     246  654.81   275.5  656.44   295.2  657.69
     305  658.41   314.8  659.29   324.7  660.58   334.5  662.63   344.3  665.08
     364  669.45
#Mann= 3 , 0 , 0
       0      .1       0    76.6    .045       0    96.6     .06       0
Bank Sta=76.6,96.6
XS Rating Curve= 0 ,0
Exp/Cntr=0.3,0.1

Type RM Length L Ch R = 1 ,4617.9  ,356.9,342.5,327.5
XS GIS Cut Line= 2
     1690050.013      493330.932     1689407.347      493193.949
#Sta/Elev= 30
       0  757.25    39.2   750.5    58.8  746.61    68.6  744.98   107.9  741.37
   117.7  740.06   127.5     738   137.3  735.24   147.1  732.12   156.9  728.42
   166.7  723.93   186.3  714.12   196.2  709.81   225.6  698.77   245.2  691.18
   323.6   659.5   333.4  655.87   353.1  649.07   362.9  646.38   372.7  645.35
   373.7645.3586   393.7645.7872   529.6  650.14   549.2  651.22     559  652.35
   608.1  660.76   617.9  662.54   627.7  664.81   637.5  668.19   657.1  676.87
#Mann= 3 , 0 , 0
       0      .1       0   373.7    .045       0   393.7     .06       0
Bank Sta=373.7,393.7
XS Rating Curve= 0 ,0
Exp/Cntr=0.3,0.1

Type RM Length L Ch R = 1 ,4275.4  ,294.6,294,289.3
XS GIS Cut Line= 3
     1689918.685      492779.239     1689692.677      492883.903
     1689359.318      493038.281
#Sta/Elev= 30
       0  678.94     9.6  677.69    19.2  676.14    28.7  674.21    38.3  671.76
    57.5  665.86    67.1  663.14    76.6  660.83    95.8  656.72   105.4  654.75
     115  653.19   124.5   652.5   134.1  652.16     182  650.91   239.5  649.59
   326.4  647.42   403.8  645.35   422.2644.7334   432.8  644.51   442.2644.8726
   452.1  646.53   461.8  648.68   481.1  652.57   490.8  655.08   500.4  658.33
   510.1  662.14   519.8  666.09   548.8  677.95   577.8  689.98   616.4  706.59
#Mann= 3 , 0 , 0
       0     .06       0   422.2    .045       0   442.2      .1       0
Bank Sta=422.2,442.2
XS Rating Curve= 0 ,0
Exp/Cntr=0.3,0.1

Type RM Length L Ch R = 1 ,3981.4  ,290.7,298,304.7
XS GIS Cut Line= 3
      1689765.58      492480.903     1689582.071      492594.132
     1689272.294      492785.271
#Sta/Elev= 30
       0  705.63    39.2  688.66    68.6  676.12    78.4     672    88.2  668.29
      98  665.23   107.8  662.66   127.4  657.97   156.8  651.13   166.6  649.18
   176.4     648   225.5  645.64   245.1  644.87     255  644.62   274.7  644.36
   387.6 644.287   392.7  644.27   402.6  644.55   407.6 645.175   412.4  645.78
   422.2  647.92   432.1  650.72   441.9   654.7   451.7  659.76   471.4  669.77
   481.2  674.64   500.9  684.27   530.4  697.97   550.1  706.85   579.6   719.9
#Mann= 3 , 0 , 0
       0     .06       0   387.6    .045       0   407.6      .1       0
Bank Sta=387.6,407.6
XS Rating Curve= 0 ,0
Exp/Cntr=0.3,0.1

Type RM Length L Ch R = 1 ,3683.5  ,302.2,302.6,296
XS GIS Cut Line= 3
     1689689.077      492331.833     1689485.616      492381.675
     1689129.399      492468.937
#Sta/Elev= 30
       0  688.69      19  683.01    38.1  677.77    47.6  674.87    66.6  668.52
    76.2  666.22    85.7   664.6    95.2  663.15   123.8  658.93   152.4  654.86
   161.9  653.78   171.4  653.06   286.7  647.58   325.3  645.98   380.8644.0475
   392.8  643.74   400.8644.1031   402.5  644.18   412.2   645.6   421.8   648.1
   431.5  651.86   441.1   656.6   450.8  661.66   479.7  677.08     499  687.02
     528  701.72   547.3  712.07   556.9  717.41   566.6  722.62   576.2  727.52
#Mann= 3 , 0 , 0
       0     .06       0   380.8    .045       0   400.8      .1       0
Bank Sta=380.8,400.8
XS Rating Curve= 0 ,0
Exp/Cntr=0.3,0.1

Type RM Length L Ch R = 1 ,3380.9  ,302.7,303.8,302.1
XS GIS Cut Line= 3
     1689539.997      492019.345     1689384.508      492085.845
     1689035.593      492235.069
#Sta/Elev= 27
       0  713.88    56.4  689.59   122.1  662.77   150.3     651   159.7   647.5
   169.1  645.39   178.8  644.62   237.2  643.58   276.2   642.8   295.6  642.56
   329.2642.3809   334.5  642.36   349.2642.4476     354  642.52   363.7  643.06
   373.4  644.09   383.2  645.79   392.9  648.73   402.6  652.94   412.4  657.74
   441.6  672.31   470.8   687.1   480.5  691.82   490.2   696.1     500  700.08
   509.7  703.91   548.6  718.76
#Mann= 3 , 0 , 0
       0     .06       0   329.2    .045       0   349.2      .1       0
Bank Sta=329.2,349.2
XS Rating Curve= 0 ,0
Exp/Cntr=0.3,0.1

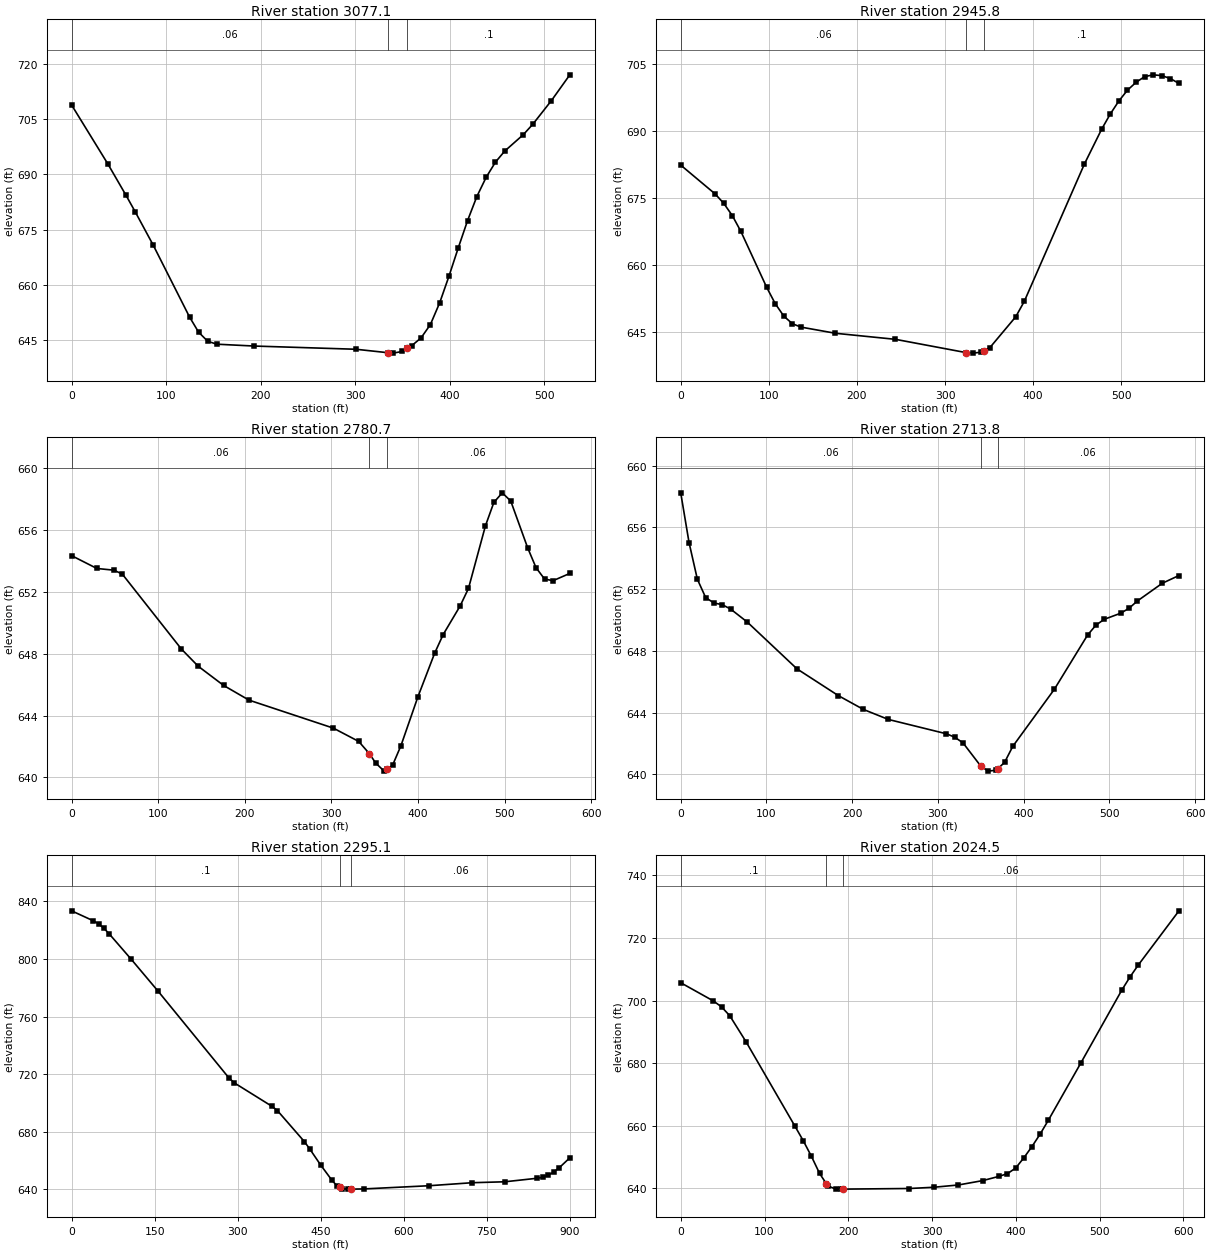
Type RM Length L Ch R = 1 ,3077.1  ,128.9,131.2,132.5
XS GIS Cut Line= 3
     1689388.056       491745.27     1689241.569       491817.29
     1688914.821      491977.936
#Sta/Elev= 30
       0  708.88    38.4  692.84    57.6  684.32    67.2   679.9    86.4  670.77
   124.8  651.25   134.4  647.12     144  644.65   153.6  643.84   192.8  643.34
     301  642.46   335.2641.5121   340.4  641.41   350.2  641.88   355.2642.6738
     360  643.43   369.9  645.57   379.7  649.16   389.6  655.11   399.4  662.33
   409.2     670   419.1  677.46   428.9  683.98   438.8  689.23   448.6  693.34
   458.4  696.34   478.1  700.81     488   703.6   507.7  710.02   527.3  717.07
#Mann= 3 , 0 , 0
       0     .06       0   335.2    .045       0   355.2      .1       0
Bank Sta=335.2,355.2
XS Rating Curve= 0 ,0
Exp/Cntr=0.3,0.1

Type RM Length L Ch R = 1 ,2945.8  ,164.3,165.1,165.8
XS GIS Cut Line= 2
     1689340.714      491655.535     1688814.595      491862.601
#Sta/Elev= 30
       0  682.44      39  675.99    48.7  673.91    58.5  671.14    68.2  667.61
    97.5  655.07   107.2  651.41     117   648.6   126.7   646.9   136.5  646.14
   175.5  644.76   243.7   643.4   324.1640.4157   331.4  640.31   341.2  640.52
   344.1640.8288   350.9  641.56   380.2  648.46   389.9  651.92   458.2  682.73
   477.7   690.5   487.4  693.87   497.2  696.81   506.9  699.22   516.7  700.99
   526.4  702.26   536.2  702.67   545.9  702.49   555.6  701.84   565.4  700.74
#Mann= 3 , 0 , 0
       0     .06       0   324.1    .045       0   344.1      .1       0
Bank Sta=324.1,344.1
XS Rating Curve= 0 ,0
Exp/Cntr=0.3,0.1

Type RM Length L Ch R = 1 ,2780.7  ,66.7,66.9,66.5
XS GIS Cut Line= 2
      1689302.04      491518.545     1688757.397        491703.7
#Sta/Elev= 30
       0  654.34    29.2  653.51    48.8   653.4    58.5  653.15   126.8   648.3
   146.2  647.19   175.5  645.95   204.8     645   302.2  643.19   331.5  642.33
   343.9641.5316     351  640.94   360.8  640.41   363.9640.5262   370.5  640.78
   380.2  642.05   399.8  645.21   419.2  648.04     429  649.24   448.5  651.08
   458.2  652.22   477.8  656.27   487.5  657.78   497.2   658.4     507  657.87
   526.5  654.85   536.2  653.56     546  652.83   555.8  652.72   575.2  653.19
#Mann= 3 , 0 , 0
       0     .06       0   343.9    .045       0   363.9     .06       0
Bank Sta=343.9,363.9
XS Rating Curve= 0 ,0
Exp/Cntr=0.3,0.1

Type RM Length L Ch R = 1 ,2713.8  ,429.6,418.8,403
XS GIS Cut Line= 2
     1689284.184      491455.294     1688733.948       491642.35
#Sta/Elev= 30
       0  658.24     9.7  655.02    19.4  652.64    29.1  651.45    38.7   651.1
    48.4  650.99    58.1  650.71    77.5  649.87   135.6  646.83     184  645.09
   213.1   644.2   242.2  643.55     310  642.62   319.6   642.4   329.3  642.03
   349.7  640.55   358.4   640.2   368.1  640.26   369.7640.3441   377.8  640.77
   387.4  641.81   435.9  645.51   474.6  649.02   484.3  649.66     494  650.04
   513.4  650.44     523  650.76   532.7  651.23   561.8  652.38   581.2  652.88
#Mann= 3 , 0 , 0
       0     .06       0   349.7    .045       0   369.7     .06       0
Bank Sta=349.7,369.7
XS Rating Curve= 0 ,0
Exp/Cntr=0.3,0.1

Type RM Length L Ch R = 1 ,2295.1  ,270.6,270.6,270.3
XS GIS Cut Line= 2
     1689103.429      490834.547     1688551.719      491546.165
#Sta/Elev= 30
       0  833.37    39.2  826.46    48.9  824.34    58.7  821.14    68.5  817.16
   107.7  799.78   156.6  777.47   283.8  717.64   293.6  714.06   362.1  697.68
   371.9  694.73   420.9   673.1   430.6  667.97   450.2   656.9   469.8  646.73
   479.6  642.39   484.8641.4033   489.4  640.53   499.2   640.2   504.8   640.2
   528.5  640.34     646  642.56   724.3  644.66     783   645.3   841.7  647.76
   851.5  648.44   861.3  649.83   871.1  652.02   880.9  654.91   900.4  661.93
#Mann= 3 , 0 , 0
       0      .1       0   484.8    .045       0   504.8     .06       0
Bank Sta=484.8,504.8
XS Rating Curve= 0 ,0
Exp/Cntr=0.3,0.1

Type RM Length L Ch R = 1 ,2024.5  ,335.4,335.1,333.4
XS GIS Cut Line= 2
     1688686.688      490938.327     1688322.334      491408.285
#Sta/Elev= 30
       0  705.69      39  699.86    48.7  697.97    58.5  695.15      78   686.8
   136.5  659.75   146.2  655.21     156  650.19   165.7  644.75   173.9641.4031
   175.5  640.75   185.2  639.73   191.4  639.72   193.9  639.72     273  639.92
   302.2  640.32   331.4  641.05   360.7  642.46   380.2  643.83   389.9  644.67
   399.7  646.45   409.4   649.7   419.2  653.34   428.9   657.3   438.7  661.73
   477.7  680.13   526.4  703.34   536.2  707.55   545.9   711.3   594.6  728.67
#Mann= 3 , 0 , 0
       0      .1       0   173.9    .045       0   193.9     .06       0
Bank Sta=173.9,193.9
XS Rating Curve= 0 ,0
Exp/Cntr=0.3,0.1

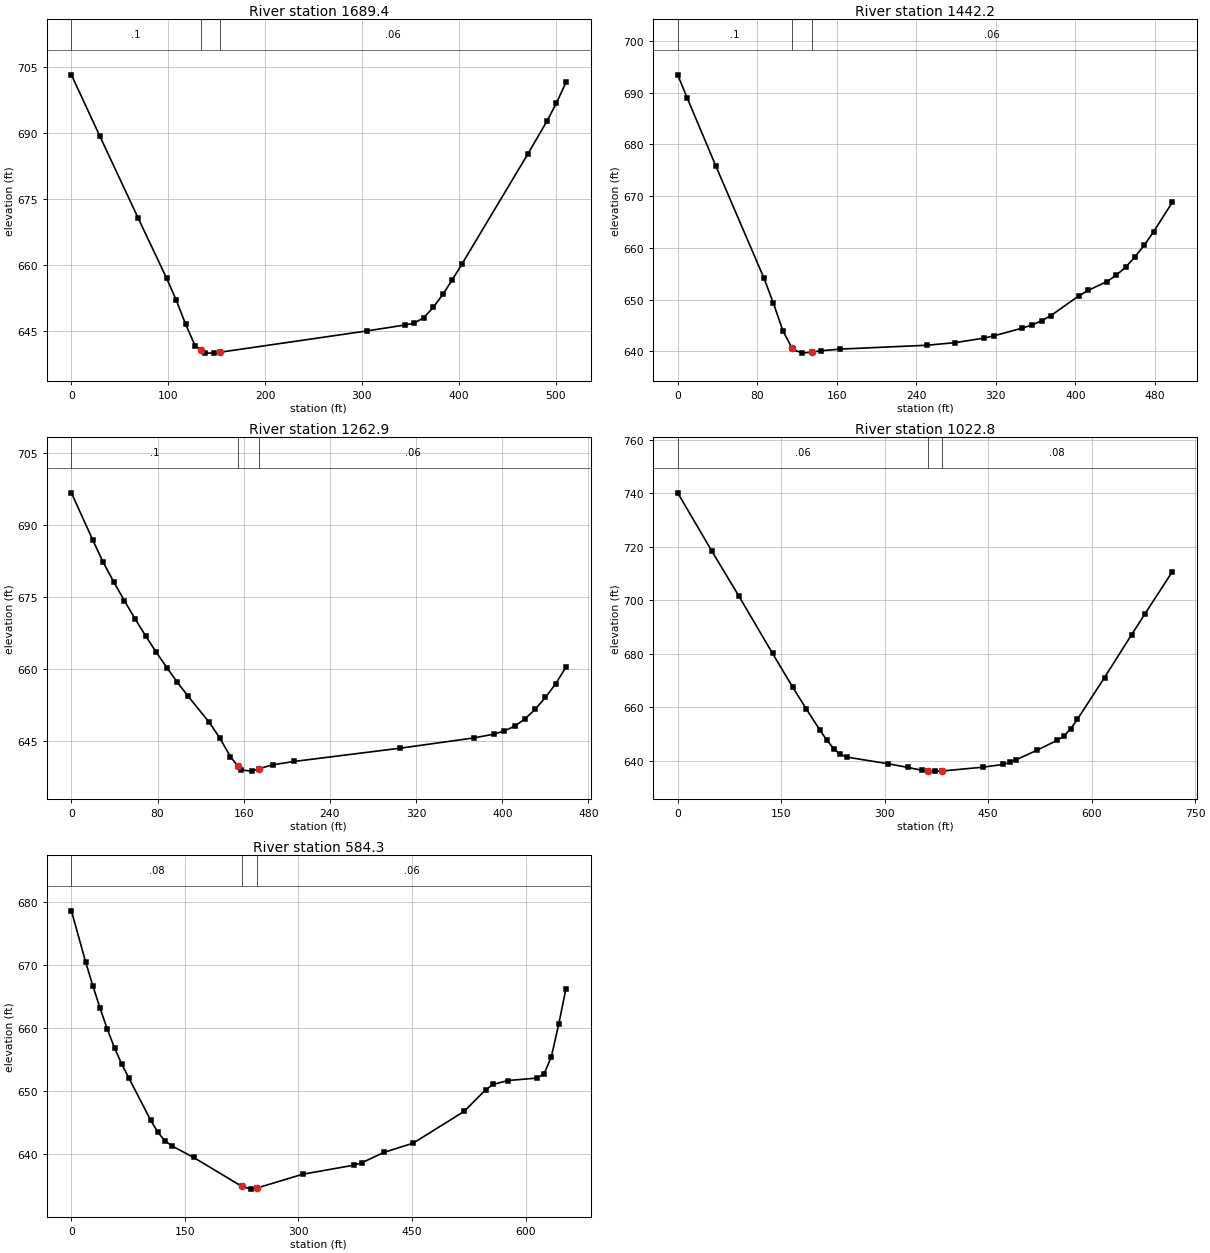
Type RM Length L Ch R = 1 ,1689.4  ,238.5,247.2,255.5
XS GIS Cut Line= 3
     1688372.942      490793.458     1688162.028      491090.126
     1688077.048      491209.658
#Sta/Elev= 23
       0  703.25    29.5  689.22    68.9  670.65    98.4   656.9   108.2  651.98
     118  646.43   127.9   641.5   133.5640.5735   137.7  639.88   147.6  639.89
   153.5640.0859     305  644.93   344.3  646.28   354.2  646.73     364  647.98
   373.8  650.33   383.6  653.26   393.3  656.58   403.1  660.09   471.6  685.32
   491.1  692.73   500.9  696.83   510.7  701.52
#Mann= 3 , 0 , 0
       0      .1       0   133.5    .045       0   153.5     .06       0
Bank Sta=133.5,153.5
XS Rating Curve= 0 ,0
Exp/Cntr=0.3,0.1

Type RM Length L Ch R = 1 ,1442.2  ,176.3,179.3,182.5
XS GIS Cut Line= 3
     1688227.865      490663.294     1687919.951      490861.123
     1687809.379      490932.163
#Sta/Elev= 29
       0  693.42     9.6  688.93    38.5  675.75    86.7  654.18    96.3  649.28
   105.9  643.93   114.8640.7095   115.6  640.42   125.2  639.67   134.8  639.88
   144.5  640.13   163.7  640.45   250.4  641.19   279.3   641.7   308.2  642.58
   317.8     643   346.7  644.51   356.4  645.12     366  645.91   375.4  646.93
   403.5  650.74   412.9   651.8   431.7  653.48   441.1  654.73   450.5  656.27
   459.9  658.28   469.2   660.5   478.6   663.1   497.4  668.79
#Mann= 3 , 0 , 0
       0      .1       0   114.8    .045       0   134.8     .06       0
Bank Sta=114.8,134.8
XS Rating Curve= 0 ,0
Exp/Cntr=0.3,0.1

Type RM Length L Ch R = 1 ,1262.9  ,239.1,240.1,242
XS GIS Cut Line= 3
     1688146.117      490533.108     1687818.503      490691.792
     1687732.928      490733.242
#Sta/Elev= 30
       0  696.76    19.7     687    29.5   682.3    39.4  678.18    49.2   674.3
      59  670.56    68.9  666.98    78.7  663.61    88.6  660.38    98.4   657.3
   108.2  654.46   127.9  649.01   137.7  645.75   147.6  641.84   154.4639.9243
   157.4  639.08   167.2  638.83   174.4639.3527   186.9  640.14   206.6  640.84
     305   643.6   373.5  645.74   392.6  646.54     402  647.22   411.6  648.18
   421.1  649.72   430.6  651.71   440.1  654.19   449.6  657.04   459.1  660.46
#Mann= 3 , 0 , 0
       0      .1       0   154.4    .045       0   174.4     .06       0
Bank Sta=154.4,174.4
XS Rating Curve= 0 ,0
Exp/Cntr=0.3,0.1

Type RM Length L Ch R = 1 ,1022.8  ,426.4,438.5,443
XS GIS Cut Line= 2
     1688188.665      490245.675     1687559.161      490588.615
#Sta/Elev= 30
       0  740.16    49.1  718.56    88.4   701.7   137.5  680.14   166.9  667.45
   186.6   659.3   206.2  651.47     216   647.8   225.9   644.6   235.7  642.39
   245.5  641.39   304.4  638.94   333.9  637.54   353.5  636.51   362.7636.2753
   373.2  636.16   382.7636.1989   441.9  637.62   471.4  638.65   481.2   639.4
     491  640.44   520.5  643.94   549.9  647.64   559.7   649.2   569.6  651.95
   579.4  655.54   618.7  671.14   657.9  687.14   677.6  695.06   716.9  710.65
#Mann= 3 , 0 , 0
       0     .06       0   362.7    .045       0   382.7     .08       0
Bank Sta=362.7,382.7
XS Rating Curve= 0 ,0
Exp/Cntr=0.3,0.1

Type RM Length L Ch R = 1 ,584.3   ,591.1,584.3,572.1
XS GIS Cut Line= 4
     1688046.428      490208.915     1687789.823      490205.718
     1687643.191      490204.118     1687581.023      490446.377
#Sta/Elev= 30
       0  678.62      19  670.44    28.5  666.68      38  663.14    47.5  659.85
      57  656.88    66.5  654.34      76   652.1   104.6  645.46   114.1  643.54
   123.6  642.17   133.1  641.34   161.6  639.53   224.9634.9619   237.6  634.51
   244.9634.6732   305.5  636.87   373.9  638.32   383.7  638.69   412.9  640.33
   451.4  641.79   518.7  646.82   547.6  650.28   557.2   651.1   576.4  651.72
   614.9  652.11   624.5  652.77   634.1   655.5   643.8  660.62   653.4   666.3
#Mann= 3 , 0 , 0
       0     .08       0   224.9    .045       0   244.9     .06       0
Bank Sta=224.9,244.9
XS Rating Curve= 0 ,0
Exp/Cntr=0.3,0.1

Chan Stop Cuts=-1
Use User Specified Reach Order=0
Composite Channel Slope=5